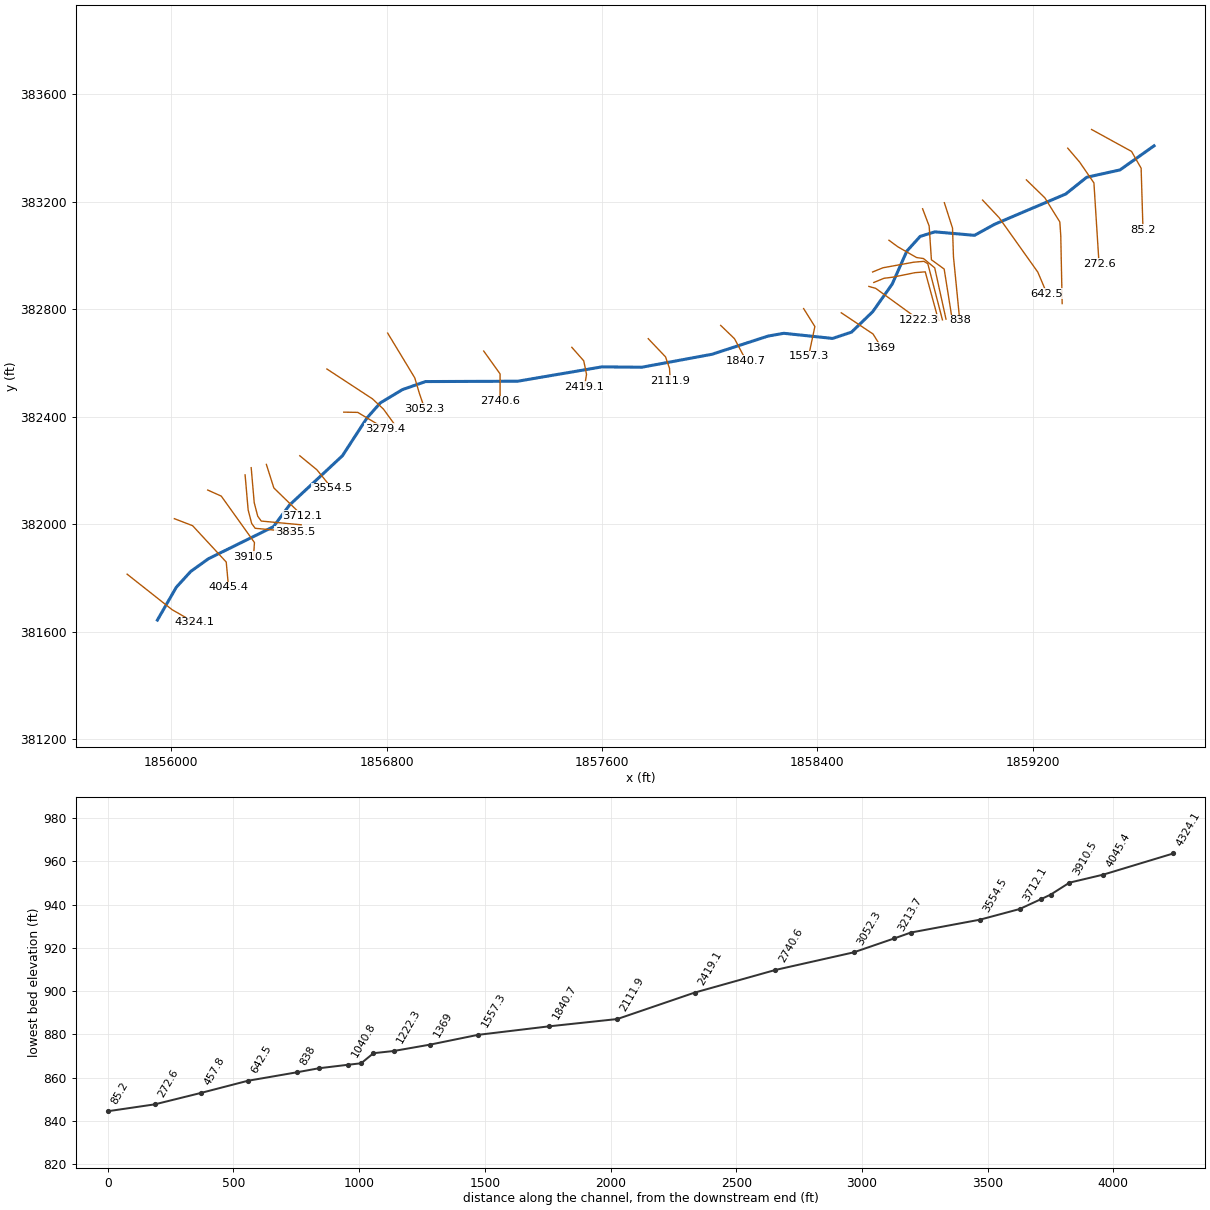
--- TENMILEFK1.prj (project) ---

Proj Title=TENMILEFK1
Current Plan=p01
Default Exp/Contr=0,0
English Units
Geom File=g01
Flow File=f01
Plan File=p01
BEGIN DESCRIPTION:
END DESCRIPTION:
DSS Export Rating Curves= 0
DSS Export Rating Curve Sorted= 0
DSS Export Volume Flow Curves= 0
DXF OffsetX= 0
DXF OffsetY= 0
DXF ScaleX= 0
DXF ScaleY= 0

--- TENMILEFK1.p01 (plan) ---

Plan Title=Floodplain
Program Version=4.00
Geom File=g01
Flow File=f01
K Sum by GR=0
Std Step Tol=0.01
Critical Tol=0.01
Num of Std Step Trials=20
Max Error Tol=0.3
Flow Tol Ratio=0.001
Split Flow NTrial=30
Split Flow Tol=0.02
Split Flow Ratio=0.02
Log Output Level=0
Friction Slope Method=1
Unsteady Friction Slope Method=2
Unsteady Bridges Friction Slope Method=1
Global Log Level=0
CheckData=False
Run HTab=0
Run UNet=0
Run PostProcess=0
UNET Theta=0
UNET Theta Warmup=0
UNET ZTol=0
UNET ZSATol=0
UNET MxIter=0
UNET MaxInSteps=0
UNET DtIC=0
UNET DtMin=0
UNET MaxCRTS=0
UNET WFStab=0
UNET SFStab=0
UNET WFX=0
UNET SFX=0
UNET DSS MLevel=0
UNET DZMax Abort=0
UNET Convert EG Bridges=0
UNET Use Existing IB Tables=0
UNET Froude Limit=0
UNET Froude Power=0
Write IC File=0
Echo Input=False
Echo Output=False
Write Detailed=0

--- TENMILEFK1.f01 (steady flow) ---

Flow Title=NFF Regression Equation
Program Version=4.10
Number of Profiles= 1
Profile Names=P100yr
River Rch & RM=TENMILEFK1,Main            ,4324.1
770.4676
River Rch & RM=TENMILEFK1,Main            ,3798.2
900.2502
River Rch & RM=TENMILEFK1,Main            ,2740.6
1249.829
River Rch & RM=TENMILEFK1,Main            ,642.5
1301.469
Boundary for River Rch & Prof#=TENMILEFK1,Main            , 1
Up Type= 0
Dn Type= 3
Dn Slope=0.02
DSS Import GetInterval= 0
DSS Import GetPeak= 0
DSS Import FillOption= 0

--- TENMILEFK1.g01 (geometry) ---

Geom Title=USGS 10m DEM
Program Version=4.10

River Reach=TENMILEFK1      ,Main
Reach XY= 30
     1855949.002      381643.607     1856019.172      381765.813
     1856072.558      381824.406     1856138.649      381872.018
      1856379.85      381991.073     1856439.745      382071.802
      1856636.36      382255.396     1856727.506      382396.021
     1856776.985      382452.011     1856859.016       382501.49
     1856944.954      382531.438     1857287.402       382532.74
     1857599.902      382586.125     1857748.339      382584.823
     1858008.756         382633.     1858217.089      382700.709
     1858275.683      382711.125     1858456.733      382692.002
      1858527.36      382715.544     1858605.835      382791.403
     1858677.992      382893.819     1858732.714      383017.115
     1858782.193      383071.802     1858836.881      383088.729
     1858984.016      383075.709     1859059.537      383117.375
     1859322.558      383229.354     1859400.683      383291.854
     1859524.381      383319.198     1859650.983      383408.924

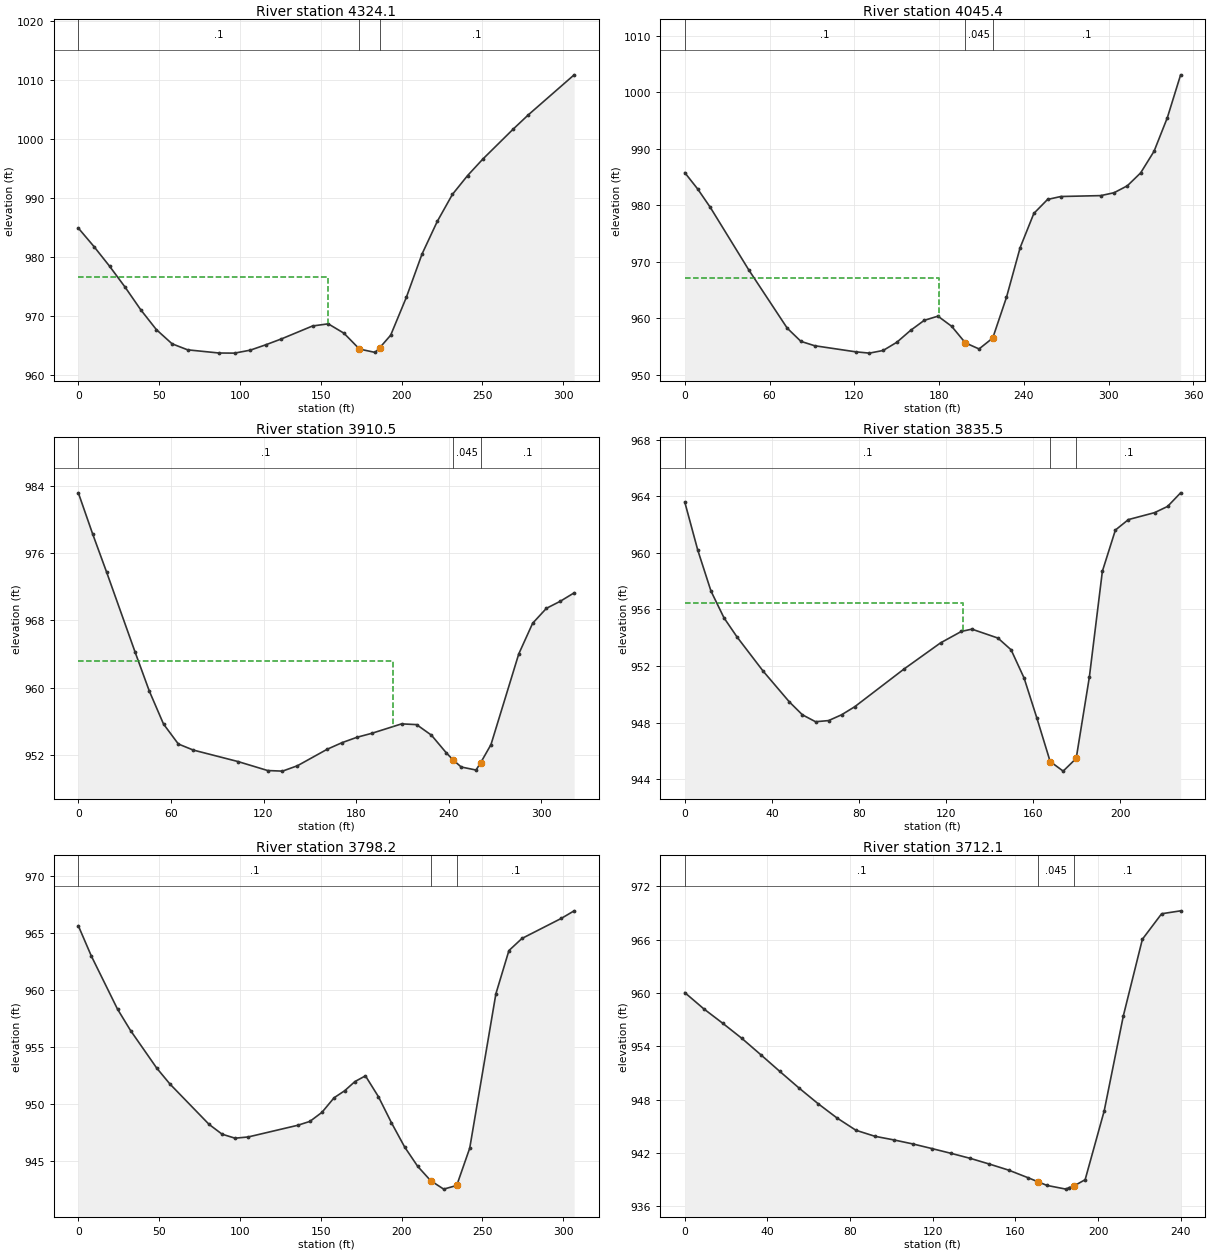
Type RM Length L Ch R = 1 ,4324.1  ,281.7,278.7,274.9
XS GIS Cut Line= 3
     1855836.642      381814.532     1856003.309      381682.588
     1856084.906      381635.713
#Sta/Elev= 29
       0  984.86     9.7  981.72    19.3   978.4      29  974.81    38.6     971
    48.3  967.62      58  965.22    67.6   964.2      87  963.66    96.6  963.64
   106.3  964.14     116  965.06   125.6  966.05   144.9  968.25   154.6  968.61
   164.3  967.02   173.9  964.33   183.6  963.76  186.32  964.52   193.2  966.68
   202.9  973.11   212.6  980.46     222  985.98   231.4  990.58   240.8  993.78
   250.2  996.57     269 1001.66   278.4 1004.09   306.7 1010.87
#Mann= 3 , 0 , 0
       0      .1       0   173.9    .045       0  186.32      .1       0
#XS Ineff= 2 , 0
          154.67   976.6
Permanent Ineff=
       F       F
Bank Sta=173.9,186.32
XS Rating Curve= 0 ,0
Exp/Cntr=0.3,0.1

Type RM Length L Ch R = 1 ,4045.4  ,137.8,134.9,130.2
XS GIS Cut Line= 4
     1856011.989       382021.13     1856079.698      381995.088
     1856204.698      381859.671     1856213.378      381765.921
#Sta/Elev= 30
       0  985.77     9.1  982.89    18.1  979.61    45.3  968.56    72.5  958.26
    82.2  955.92    91.9  955.15     121  954.07   130.7  953.84   140.4  954.31
   150.1  955.76   159.8  957.86   169.5  959.64   179.2  960.38   188.9  958.59
   198.6  955.66   208.3  954.58     218  956.51   227.7   963.7   237.4  972.51
   247.1  978.56   256.8  981.03   266.2  981.55   294.5  981.71   303.9  982.22
   313.3  983.45   322.7  985.73   332.2  989.56   341.6   995.5     351 1003.08
#Mann= 3 , 0 , 0
       0      .1       0   198.6    .045       0     218      .1       0
#XS Ineff= 2 , 0
          179.63  967.07
Permanent Ineff=
       F       F
Bank Sta=198.6,218
XS Rating Curve= 0 ,0
Exp/Cntr=0.3,0.1

Type RM Length L Ch R = 1 ,3910.5  ,41.1,75,101.2
XS GIS Cut Line= 4
     1856135.904      382127.683     1856186.251      382105.114
     1856309.515      381932.371     1856306.043      381878.551
#Sta/Elev= 30
       0  983.15     9.2  978.31    18.4   973.7    36.8  964.24      46  959.62
    55.2  955.71    64.8  953.34    74.5  952.62   103.4  951.26   122.7  950.19
   132.3  950.12     142  950.76   161.3  952.72   170.9   953.5   180.6  954.14
   190.2  954.61   209.5  955.73   219.2  955.64   228.8  954.39   238.4   952.3
  242.74  951.47   248.1  950.61   257.7  950.25  260.72  951.12   267.4  953.27
   285.4  964.03   294.4  967.67   303.3  969.44   312.3  970.28   321.3  971.28
#Mann= 3 , 0 , 0
       0      .1       0  242.74    .045       0  260.72      .1       0
#XS Ineff= 2 , 0
          203.68  963.21
Permanent Ineff=
       F       F
Bank Sta=242.74,260.72
XS Rating Curve= 0 ,0
Exp/Cntr=0.3,0.1

Type RM Length L Ch R = 1 ,3835.5  ,50.9,37.2,34.6
XS GIS Cut Line= 5
     1856274.793      382184.107     1856286.078      382053.899
     1856299.099      382003.551     1856312.119      381985.322
     1856460.557      381971.433
#Sta/Elev= 30
       0  963.58   5.978  960.18   12.02   957.3  17.998  955.41  23.976  954.06
  35.996  951.64  48.016  949.47  53.994  948.56  60.036  948.07  66.014  948.15
  71.992  948.56  78.034  949.13 100.725   951.8 117.437  953.64 127.015  954.45
 131.836  954.61 143.792  953.98 149.834  953.15 155.812  951.15 161.725   948.3
 167.768  945.26 173.745  944.58 179.723  945.48 185.766  951.22 191.744   958.7
 197.721  961.61 203.699  962.35  215.72  962.84 221.697  963.28 227.675  964.24
#Mann= 3 , 0 , 0
       0      .1       0 167.768    .045       0 179.723      .1       0
#XS Ineff= 2 , 0
         127.535  956.45
Permanent Ineff=
       F       F
Bank Sta=167.768,179.723
XS Rating Curve= 0 ,0
Skew Angle= 50
Exp/Cntr=0.3,0.1

Type RM Length L Ch R = 1 ,3798.2  ,102.4,86.2,68.4
XS GIS Cut Line= 5
     1856297.363      382211.017     1856308.647      382080.808
     1856321.668      382030.461     1856334.689      382012.232
     1856483.126      381998.343
#Sta/Elev= 30
       0  965.61   8.054  962.96  24.249  958.31  32.303  956.44  48.497  953.15
  56.638  951.76  80.887  948.22  88.941  947.36  96.995  947.01 105.135  947.12
 135.706  948.14 143.241  948.48 150.688  949.27 158.223  950.55 164.718  951.16
 171.127  951.97 177.622  952.47 185.676  950.64  193.73  948.36 201.871  946.24
 209.925  944.55 217.979  943.29 226.033  942.55 234.087  942.87 242.141  946.14
 258.335  959.66 266.389  963.44 274.443   964.5 298.692  966.25 306.746  966.92
#Mann= 3 , 0 , 0
       0      .1       0 217.979    .045       0 234.087      .1       0
Bank Sta=217.979,234.087
XS Rating Curve= 0 ,0
Skew Angle= 30
Exp/Cntr=0.3,0.1

Type RM Length L Ch R = 1 ,3712.1  ,160,157.6,154.8
XS GIS Cut Line= 3
     1856353.786      382223.169     1856381.564      382135.496
     1856487.467      382032.197
#Sta/Elev= 30
       0  960.05     9.2  958.22    18.4  956.59    27.6   954.9    36.8  953.05
      46  951.17    55.2  949.32    64.4  947.56    73.6  945.94    82.8  944.55
      92  943.87   101.2  943.46   110.5     943   119.7  942.48     129  941.94
   138.2  941.38   147.4  940.74   156.7  940.06   165.9  939.22     171  938.74
   175.2  938.34   184.4  937.92     186   938.1  188.44   938.3   193.7  938.98
   202.9  946.71   212.2  957.45   221.4  966.06   230.7  968.93   239.9  969.26
#Mann= 3 , 0 , 0
       0      .1       0     171    .045       0  188.44      .1       0
Bank Sta=171,188.44
XS Rating Curve= 0 ,0
Exp/Cntr=0.3,0.1

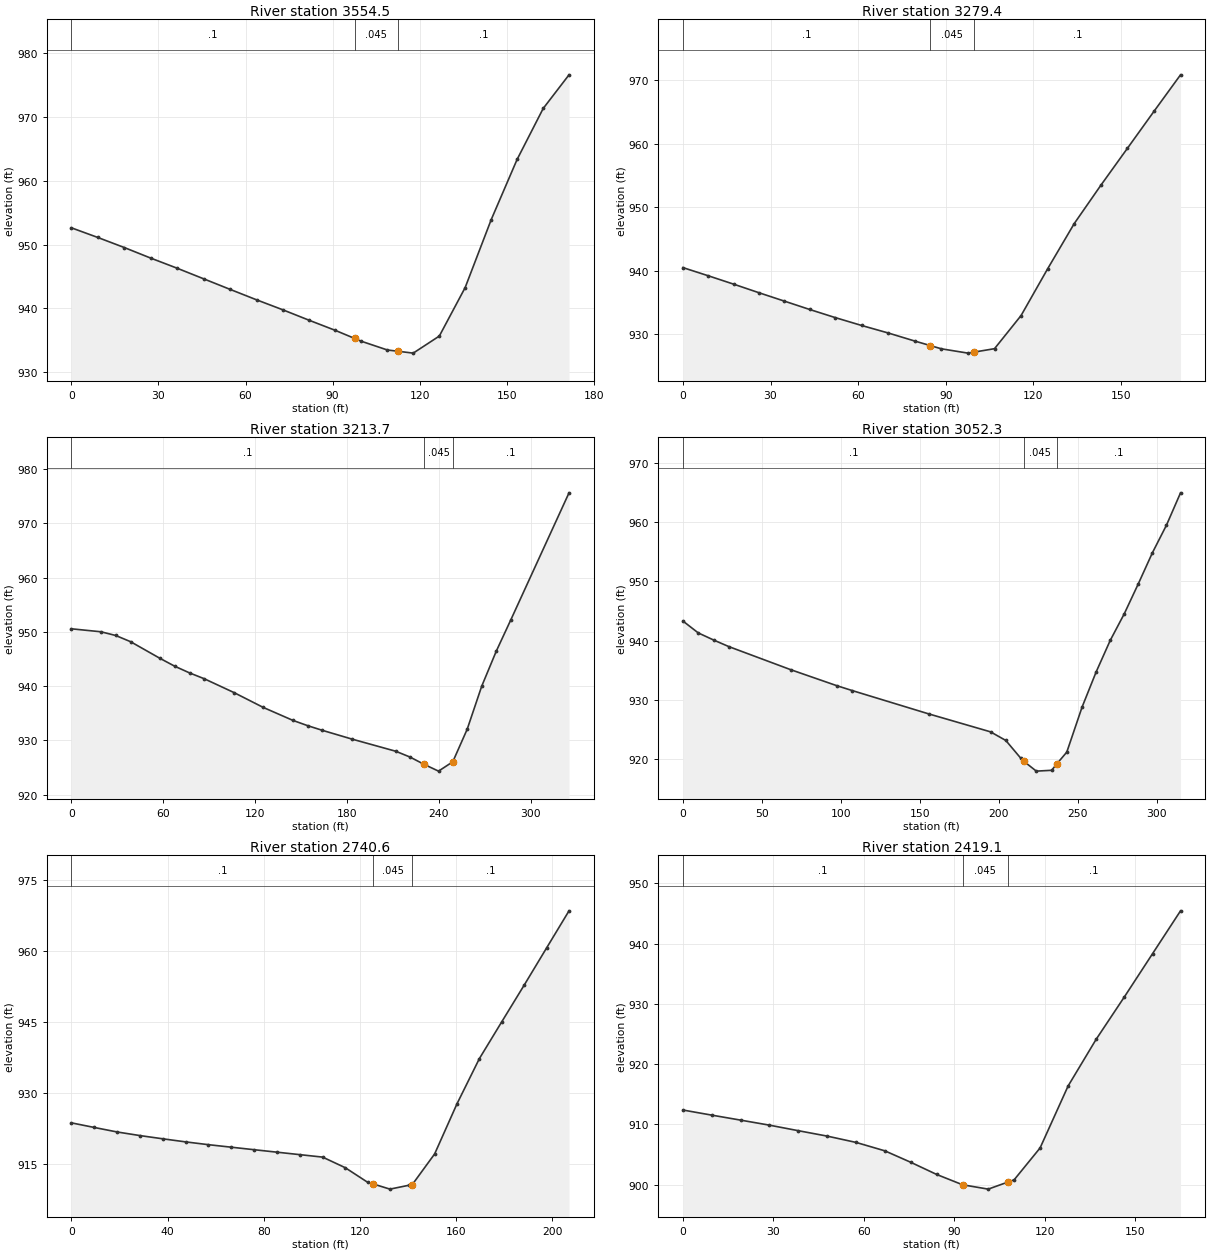
Type RM Length L Ch R = 1 ,3554.5  ,267,275.1,282.8
XS GIS Cut Line= 3
     1856477.918      382255.288     1856541.286      382203.204
      1856597.71       382133.76
#Sta/Elev= 22
       0  952.61     9.1   951.1    18.2  949.53    27.3  947.88    36.5  946.28
    45.6  944.63    54.7  942.98    63.8  941.35    72.9  939.78      82  938.14
      91  936.56    97.6  935.31    99.9  934.87   108.9   933.5   112.6   933.3
   117.8  933.01   126.8  935.68   135.7  943.26   144.7  953.91   153.6   963.3
   162.6  971.28   171.5  976.54
#Mann= 3 , 0 , 0
       0      .1       0    97.6    .045       0   112.6      .1       0
Bank Sta=97.6,112.6
XS Rating Curve= 0 ,0
Exp/Cntr=0.3,0.1

Type RM Length L Ch R = 1 ,3279.4  ,70.5,65.7,60.8
XS GIS Cut Line= 3
     1856641.113      382417.614     1856693.196      382416.746
     1856794.758      382355.982
#Sta/Elev= 22
       0  940.51     8.7  939.22    17.4   937.9      26  936.56    34.7  935.24
    43.4  933.92    52.1  932.65    61.2   931.4    70.3  930.22    79.4  928.95
    84.7  928.24    88.5  927.73    97.6  927.05    99.7  927.21   106.7  927.75
   115.8  932.97   124.9  940.33     134  947.44   143.1  953.46   152.2  959.28
   161.3   965.1   170.4  970.85
#Mann= 3 , 0 , 0
       0      .1       0    84.7    .045       0    99.7      .1       0
Bank Sta=84.7,99.7
XS Rating Curve= 0 ,0
Exp/Cntr=0.3,0.1

Type RM Length L Ch R = 1 ,3213.7  ,173.4,161.5,149.4
XS GIS Cut Line= 4
     1856578.613      382578.204     1856747.883      382467.093
     1856788.682      382428.899     1856827.744      382375.079
#Sta/Elev= 24
       0  950.57    19.3  950.02    28.9  949.34    38.6   948.2    57.8  945.13
    67.5  943.67    77.1  942.45    86.8  941.36   106.1  938.83   125.3  936.08
   144.6   933.7   154.3  932.72   163.9  931.86   183.2  930.25   211.8  928.01
   221.1  926.94   230.4  925.58   239.7  924.35     249  926.07   258.4  932.06
   267.9     940   277.4  946.45   286.9  952.22   324.9  975.62
#Mann= 3 , 0 , 0
       0      .1       0   230.4    .045       0     249      .1       0
Bank Sta=230.4,249
XS Rating Curve= 0 ,0
Exp/Cntr=0.3,0.1

Type RM Length L Ch R = 1 ,3052.3  ,318.2,311.7,305.2
XS GIS Cut Line= 4
     1856804.307      382711.885     1856905.001      382545.218
     1856921.494      382489.663      1856941.46      382430.635
#Sta/Elev= 24
       0   943.3     9.7  941.29    19.5  940.08    29.2  938.96    68.2  935.07
    97.4  932.36   107.1  931.54   155.8  927.57   194.7  924.55   204.4  923.09
     214  920.04  215.77  919.57   223.7   917.9   233.4  918.04  236.85  919.18
     243  921.12   252.7  928.76   261.6   934.7   270.5  940.03   279.4  944.54
   288.3  949.62   297.2  954.86   306.1  959.53     315     965
#Mann= 3 , 0 , 0
       0      .1       0  215.77    .045       0  236.85      .1       0
Bank Sta=215.77,236.85
XS Rating Curve= 0 ,0
Exp/Cntr=0.3,0.1

Type RM Length L Ch R = 1 ,2740.6  ,316.6,321.5,324.6
XS GIS Cut Line= 3
     1857161.078      382645.044     1857221.842      382559.975
     1857221.842      382457.544
#Sta/Elev= 25
       0  923.72     9.5  922.75      19   921.8    28.5  921.04      38  920.36
    47.5  919.71      57  919.12    66.5  918.59      76  918.06    85.5  917.54
      95  917.02   104.5   916.5   113.9  914.27   123.2   911.2   125.6  910.83
   132.5  909.75   140.6  910.59   141.8  910.71   151.1  917.17   160.4  927.74
   169.7  937.26     179  945.01   188.4   952.8   197.7  960.62     207  968.42
#Mann= 3 , 0 , 0
       0      .1       0   125.6    .045       0   141.8      .1       0
Bank Sta=125.6,141.8
XS Rating Curve= 0 ,0
Exp/Cntr=0.3,0.1

Type RM Length L Ch R = 1 ,2419.1  ,304.3,307.2,311.3
XS GIS Cut Line= 4
     1857488.335      382658.933     1857532.606      382608.586
     1857543.022      382558.239      1857535.21      382512.232
#Sta/Elev= 20
       0  912.39     9.6  911.54    19.2  910.71    28.7  909.88    38.3  908.96
    47.9  908.06    57.5  907.01      67  905.62    75.6  903.72    84.2   901.7
    92.8  899.99   101.3  899.27   107.8  900.44   109.9  900.82   118.5   906.1
   127.8  916.38   137.1  924.12   146.5  931.18   155.8  938.31   165.1  945.43
#Mann= 3 , 0 , 0
       0      .1       0    92.8    .045       0   107.8      .1       0
Bank Sta=92.8,107.8
XS Rating Curve= 0 ,0
Exp/Cntr=0.3,0.1

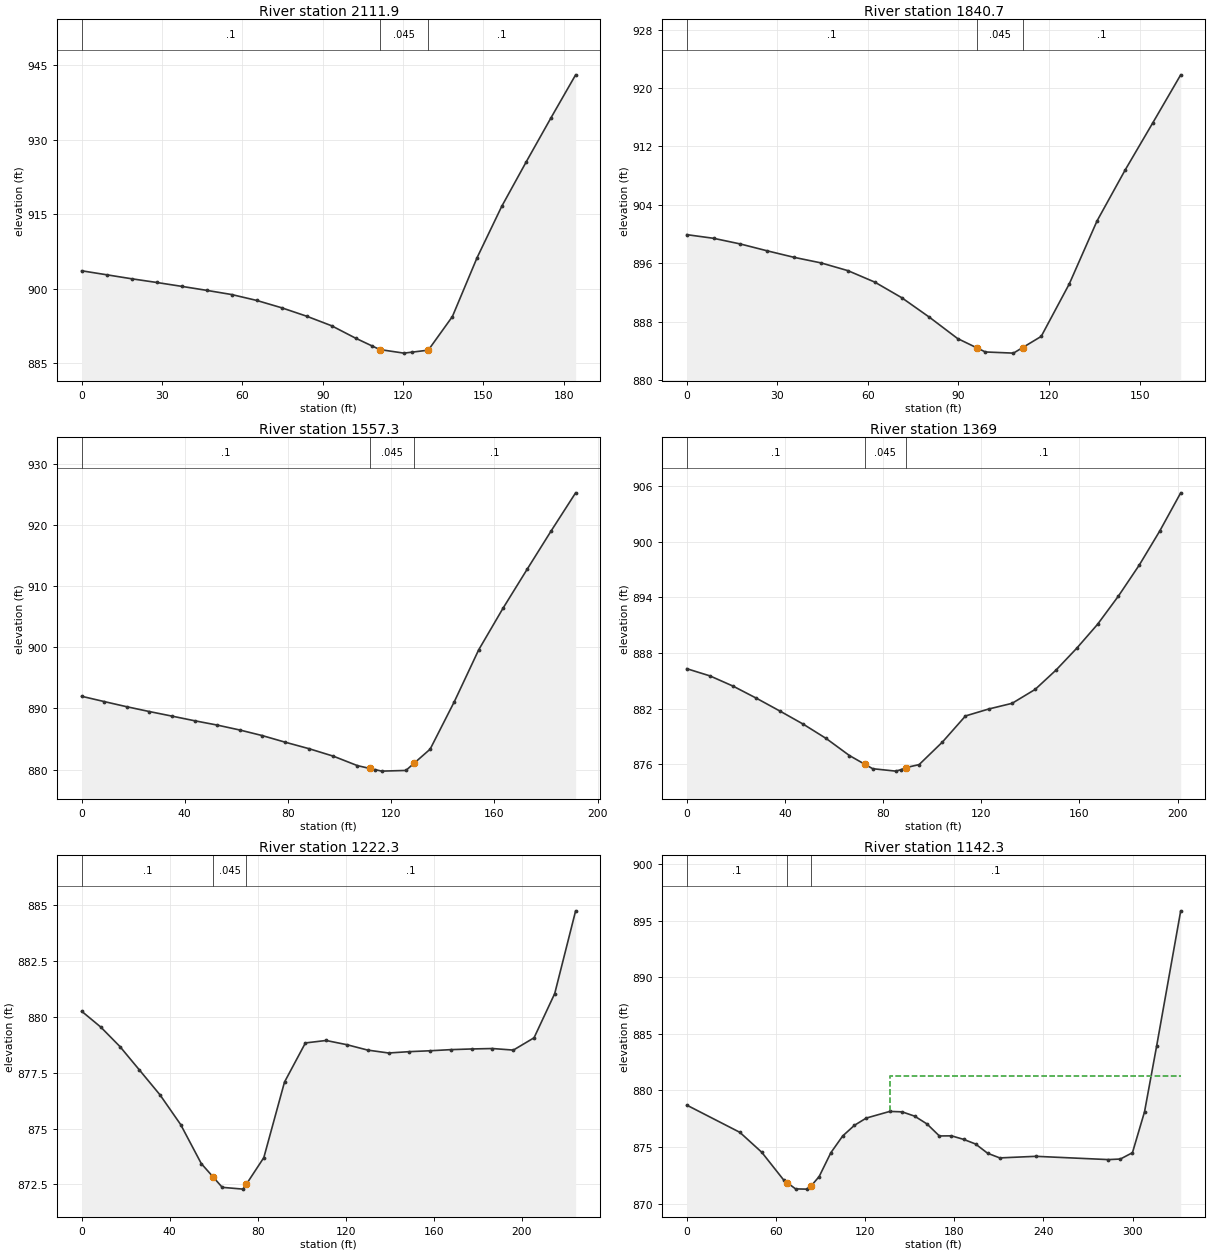
Type RM Length L Ch R = 1 ,2111.9  ,267.2,271.2,274.5
XS GIS Cut Line= 4
     1857772.189      382691.051     1857836.425      382623.343
     1857851.182      382580.808     1857853.786      382534.801
#Sta/Elev= 23
       0  903.64     9.3  902.84    18.7  902.03      28  901.29    37.3  900.51
    46.7   899.7      56  898.86    65.3  897.68    74.7  896.19      84   894.5
    93.3  892.58   102.3  890.07   108.4  888.52   111.3  887.79   120.3  887.07
   123.4  887.27   129.4  887.67   138.4  894.43   147.6  906.26   156.8  916.59
     166   925.6   175.2  934.42   184.4  943.07
#Mann= 3 , 0 , 0
       0      .1       0   111.3    .045       0   129.4      .1       0
Bank Sta=111.3,129.4
XS Rating Curve= 0 ,0
Exp/Cntr=0.3,0.1

Type RM Length L Ch R = 1 ,1840.7  ,299.3,283.4,267.6
XS GIS Cut Line= 3
     1858041.286      382740.531     1858092.501      382691.051
     1858135.904      382609.454
#Sta/Elev= 21
       0  899.92     8.9  899.42    17.8  898.64    26.7   897.7    35.6  896.81
    44.5  896.05    53.4  894.99    62.3  893.42    71.2  891.29    80.4  888.61
    89.7   885.7    96.3  884.38    98.9  883.86   108.2   883.7   111.3  884.47
   117.4  885.99   126.7  893.18   135.9  901.81   145.2  908.77   154.4  915.26
   163.6   921.8
#Mann= 3 , 0 , 0
       0      .1       0    96.3    .045       0   111.3      .1       0
Bank Sta=96.3,111.3
XS Rating Curve= 0 ,0
Exp/Cntr=0.3,0.1

Type RM Length L Ch R = 1 ,1557.3  ,161.2,188.4,215.5
XS GIS Cut Line= 3
     1858349.446      382803.031     1858391.113       382736.19
     1858367.675      382625.947
#Sta/Elev= 25
       0  891.98     8.8  891.11    17.5  890.27    26.2  889.49      35  888.74
    43.8  887.98    52.5  887.28    61.3  886.47      70  885.56    78.8  884.49
    88.2  883.41    97.6  882.19   106.9  880.65  111.78  880.18   113.8  879.99
   116.3  879.75   125.7  879.86   128.8  881.01   135.1  883.34   144.5  891.12
   153.9  899.55   163.3  906.33   172.7  912.73   182.1  919.06   191.5  925.22
#Mann= 3 , 0 , 0
       0      .1       0  111.78    .045       0   128.8      .1       0
Bank Sta=111.78,128.8
XS Rating Curve= 0 ,0
Exp/Cntr=0.3,0.1

Type RM Length L Ch R = 1 ,1369    ,147.6,146.7,145.8
XS GIS Cut Line= 3
     1858489.203      382787.406     1858607.258      382708.413
     1858638.508      382658.065
#Sta/Elev= 26
       0  886.31     9.5  885.53    18.9  884.43    28.4  883.13    37.9  881.76
    47.4  880.35    56.8   878.8    66.3  876.96    72.5  876.03    75.8  875.54
    85.2  875.28    87.5  875.45   89.46  875.67    94.7  875.98   104.2  878.41
   113.6  881.22   123.1  881.97   132.6  882.58     142  884.08   150.5  886.16
     159  888.53   167.4  891.08   175.9  894.12   184.4  897.46   192.8  901.15
   201.3  905.24
#Mann= 3 , 0 , 0
       0      .1       0    72.5    .045       0   89.46      .1       0
Bank Sta=72.5,89.46
XS Rating Curve= 0 ,0
Exp/Cntr=0.3,0.1

Type RM Length L Ch R = 1 ,1222.3  ,60,80,100
XS GIS Cut Line= 3
     1858591.633      382885.496     1858616.807      382878.551
      1858777.25      382761.893
#Sta/Elev= 27
       0  880.25     8.7  879.54    17.4  878.67    26.1  877.64    35.6  876.51
      45  875.18    54.4  873.43    59.8  872.83    63.9  872.37    73.4  872.29
    74.8   872.5    82.8   873.7    92.2  877.08   101.7  878.83   111.1  878.94
   120.6  878.75     130  878.51   139.5  878.38   148.9  878.44   158.4  878.48
   167.8  878.53   177.2  878.56   186.7  878.58   196.2  878.51   205.6  879.06
     215  881.04   224.5  884.74
#Mann= 3 , 0 , 0
       0      .1       0    59.8    .045       0    74.8      .1       0
Bank Sta=59.8,74.8
XS Rating Curve= 0 ,0
Exp/Cntr=0.3,0.1

Type RM Length L Ch R = 1 ,1142.3  ,46.5,49.2,50.8
XS GIS Cut Line= 6
     1858609.863      382900.253     1858648.057      382915.878
     1858681.911      382920.218      1858762.64      382936.711
     1858801.043      382939.911     1858850.318      382759.029
#Sta/Elev= 30
       0  878.71  35.767   876.3  50.489  874.54  65.298  872.08  67.637  871.85
  73.266   871.3  80.627  871.28  83.762  871.57  89.114  872.39  96.995   874.5
 104.962  875.98 112.843  876.92 120.811  877.56 136.659  878.15 144.973  878.11
 153.373  877.73 161.687  877.04 170.001  875.98 178.141  875.99 186.282  875.68
 194.336  875.27 202.477  874.45 210.617  874.04 234.953  874.18  283.71  873.89
 291.764  873.94 299.905   874.5 308.045  878.12 316.186  883.93 332.381  895.88
#Mann= 3 , 0 , 0
       0      .1       0  67.637    .045       0  83.762      .1       0
#XS Ineff= 2 , 0
                         136.538          881.29
Permanent Ineff=
       F       F
Bank Sta=67.637,83.762
XS Rating Curve= 0 ,0
Skew Angle= 30
Exp/Cntr=0.3,0.1

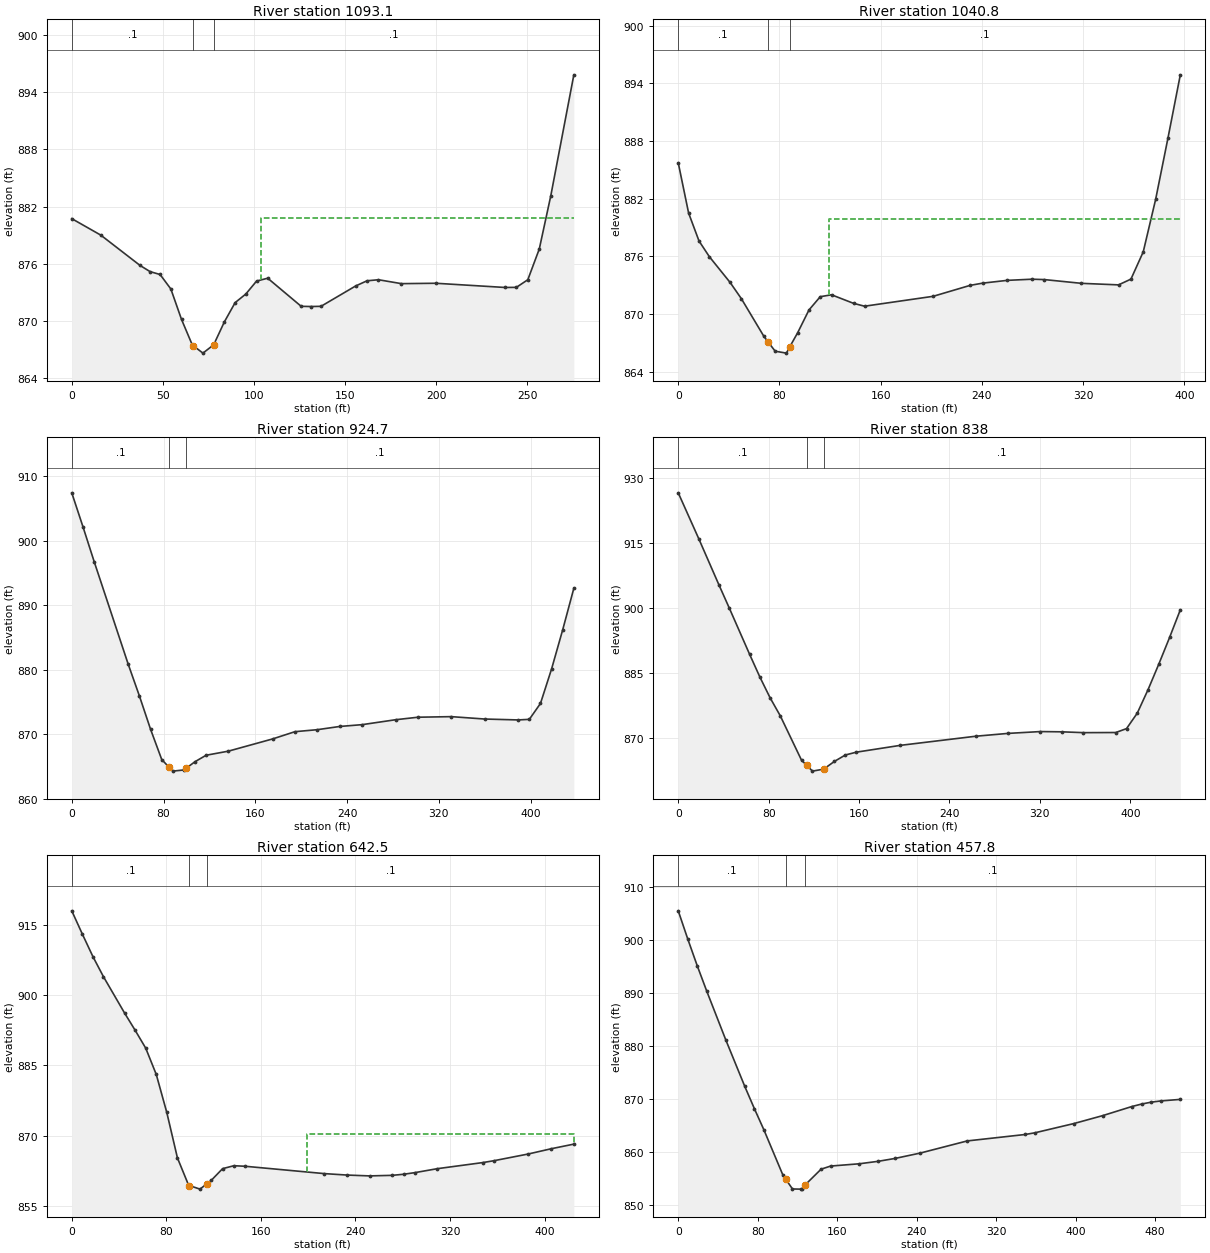
Type RM Length L Ch R = 1 ,1093.1  ,72.3,52.3,33.2
XS GIS Cut Line= 6
     1858605.522      382939.315     1858643.717       382954.94
       1858758.3      382975.774     1858796.272      382978.938
     1858810.671      382970.037     1858864.902      382761.112
#Sta/Elev= 30
       0  880.73  15.941     879  37.475  875.82  43.002  875.17  48.466  874.87
   54.38  873.35  60.229  870.16  66.143  867.48  66.657   867.4  71.992  866.62
  77.906   867.5  83.755   869.9  89.669  871.92  95.518  872.82 101.432  874.18
 107.538  874.48 125.922  871.53 131.386  871.51 136.785  871.53 155.747  873.66
 162.047  874.21 168.346  874.32 180.945  873.91 199.843  873.95 237.703  873.51
 244.002  873.52 250.301  874.32 256.601  877.55   262.9  883.12 275.563  895.82
#Mann= 3 , 0 , 0
       0      .1       0  66.657    .045       0  77.906      .1       0
#XS Ineff= 2 , 0
                         103.617          880.85
Permanent Ineff=
       F       F
Bank Sta=66.657,77.906
XS Rating Curve= 0 ,0
Skew Angle= 50
Exp/Cntr=0.3,0.1

Type RM Length L Ch R = 1 ,1040.8  ,138.6,116.1,93.7
XS GIS Cut Line= 6
     1858666.286      383057.371     1858699.272      383033.065
     1858768.717      382993.135     1858794.611      382989.327
     1858836.256      382954.654     1858878.096       382763.89
#Sta/Elev= 30
       0  885.73     8.2   880.5    16.4   877.6    24.6  875.96      41  873.28
    49.9  871.59    67.7  867.67    70.8  867.13    76.6  866.13    85.5  865.93
   88.22  866.61    94.4  868.06   103.3  870.42   112.2   871.8   121.1     872
   138.5  871.11   147.2  870.81   201.4  871.84   230.7  872.98   240.5  873.21
     260   873.5   279.6  873.62   289.3  873.58   318.6  873.19   347.9  873.03
   357.7  873.63   367.4  876.46   377.2  881.92     387  888.34   396.7  894.88
#Mann= 3 , 0 , 0
       0      .1       0    70.8    .045       0   88.22      .1       0
#XS Ineff= 2 , 0
                           119.4          879.85
Permanent Ineff=
       F       F
Bank Sta=70.8,88.22
XS Rating Curve= 0 ,0
Exp/Cntr=0.3,0.1

Type RM Length L Ch R = 1 ,924.7   ,87.3,86.7,86
XS GIS Cut Line= 5
     1858791.286      383174.558     1858815.592      383110.322
     1858823.959      382984.818     1858871.338      382950.257
     1858900.318      382768.057
#Sta/Elev= 29
       0  907.42     9.8  902.14    19.6  896.72    49.1  880.92    58.9  875.98
    68.7  870.78    78.4  866.11    84.9  864.89      88  864.31    97.7  864.49
    99.9  864.78   107.4  865.77   117.1  866.77   136.4   867.4   175.1   869.3
   194.5  870.42     214  870.73   233.6  871.23   253.1  871.51   282.2  872.27
   301.7  872.66   330.8  872.75   359.9  872.38     389  872.24   398.8  872.33
   408.5  874.79   418.2  880.14   427.9  886.21   437.6  892.64
#Mann= 3 , 0 , 0
       0      .1       0    84.9    .045       0    99.9      .1       0
Bank Sta=84.9,99.9
XS Rating Curve= 0 ,0
Exp/Cntr=0.3,0.1

Type RM Length L Ch R = 1 ,838     ,181.1,195.5,208.6
XS GIS Cut Line= 4
     1858872.015      383197.128     1858902.397       383102.51
     1858905.869      382995.739     1858929.307       382758.76
#Sta/Elev= 28
       0  926.62    18.1  916.08    36.1  905.35    45.2  900.04    63.2  889.37
    72.3  884.12    81.3  879.36    90.3  875.21   109.1  864.98   113.7  863.78
   118.8  862.46   128.7  862.92   138.2   864.7   147.9  866.18   157.6  866.83
   196.5   868.4   263.4  870.51   291.9  871.16   320.5  871.58   339.6  871.52
   358.6  871.33   387.2  871.36   396.7  872.26   406.2  875.82   415.8  881.27
   425.3  887.15   434.8  893.27   444.3  899.65
#Mann= 3 , 0 , 0
       0      .1       0   113.7    .045       0   128.7      .1       0
Bank Sta=113.7,128.7
XS Rating Curve= 0 ,0
Exp/Cntr=0.3,0.1

Type RM Length L Ch R = 1 ,642.5   ,186.3,184.6,183.3
XS GIS Cut Line= 4
     1859013.942      383206.937      1859075.14      383141.833
      1859219.09      382938.977     1859252.944      382859.116
#Sta/Elev= 30
       0  918.08     8.9  913.13    17.9  908.28    26.8  903.99    44.7   896.2
    53.6  892.53    62.6  888.68    71.5  883.06    80.4  874.93    89.4  865.21
    98.9  859.34    99.4   859.3   108.5  858.53   114.4  859.69     118   860.4
   127.6  862.91   137.2  863.54   146.8  863.42   213.7  861.85   232.9  861.54
     252  861.36   271.1  861.48   280.7  861.71   290.3  862.06   309.4  862.91
   347.7  864.21   357.4  864.62   386.3  866.05   405.6  867.17   424.8  868.16
#Mann= 3 , 0 , 0
       0      .1       0    99.4    .045       0   114.4      .1       0
#XS Ineff= 2 , 0
                          199.36           870.3
Permanent Ineff=
       F       F
Bank Sta=99.4,114.4
XS Rating Curve= 0 ,0
Exp/Cntr=0.3,0.1

Type RM Length L Ch R = 1 ,457.8   ,184.7,185.2,186.2
XS GIS Cut Line= 5
     1859176.703      383282.197     1859245.279      383215.357
     1859300.943      383125.557     1859304.415      383075.209
     1859309.624      382821.737
#Sta/Elev= 30
       0  905.57     9.6  900.24    19.2  895.15    28.7  890.39    47.9  881.16
      67  872.38    76.6   868.2    86.2  864.19   105.4  855.61   108.2  854.85
     115     853   123.2  852.97   124.6  852.97  128.08  853.83   143.8  856.74
   153.4  857.33   182.2  857.76   201.4  858.23   218.2  858.77   243.5  859.78
   290.9  862.08   349.4   863.3   359.1  863.62   398.2  865.36   427.4  866.87
   456.6  868.58   466.4  869.05   476.2  869.41   485.9  869.64   505.4  869.93
#Mann= 3 , 0 , 0
       0      .1       0   108.2    .045       0  128.08      .1       0
Bank Sta=108.2,128.08
XS Rating Curve= 0 ,0
Exp/Cntr=0.3,0.1

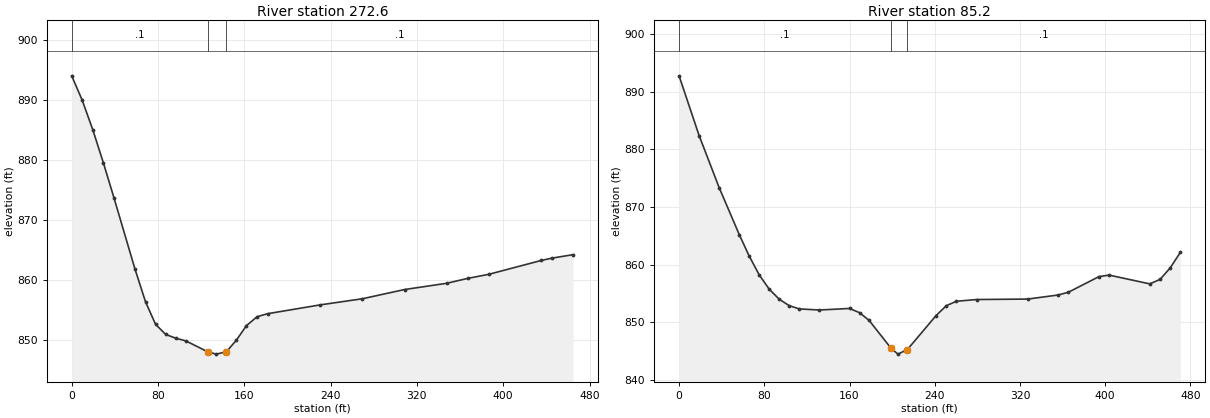
Type RM Length L Ch R = 1 ,272.6   ,189.4,187.4,185.4
XS GIS Cut Line= 4
     1859330.349      383400.253     1859374.619      383348.169
     1859427.571      383270.913     1859446.668      382968.829
#Sta/Elev= 27
       0  894.09     9.8  889.98    19.5   885.1    29.3  879.59    39.1  873.76
    58.6  861.86    68.4  856.38    77.7  852.62    87.1  850.93    96.4   850.3
   105.8  849.85   125.9  848.04   133.9  847.64   143.3  848.02   152.6  849.96
     162   852.4   171.8  853.88   181.6  854.39   230.4  855.86   269.4  856.88
   308.5  858.42   347.5  859.46   367.1  860.28   386.6  860.96   435.4  863.28
   445.2  863.66   464.7  864.24
#Mann= 3 , 0 , 0
       0      .1       0   125.9    .045       0   143.3      .1       0
Bank Sta=125.9,143.3
XS Rating Curve= 0 ,0
Exp/Cntr=0.3,0.1

Type RM Length L Ch R = 1 ,85.2    ,82.4,85.2,88
XS GIS Cut Line= 4
      1859418.89      383469.697     1859567.328        383388.1
     1859602.918        383325.6     1859609.863      383096.433
#Sta/Elev= 30
       0  892.77    18.8   882.4    37.6  873.37    56.5   865.2    65.9  861.45
    75.3  858.19    84.7  855.71    94.1  853.97   103.5  852.86   112.9   852.3
   131.8  852.11     160  852.38   169.4  851.65   178.4  850.31   198.7  845.54
   205.4  844.45   214.3  845.24   241.3  851.15   250.9  852.86   260.4  853.63
   279.5  853.93   327.3  854.01     356  854.72   365.5   855.2   394.2  857.91
   403.7  858.17   441.9  856.65   451.5  857.42     461   859.4   470.6  862.12
#Mann= 3 , 0 , 0
       0      .1       0   198.7    .045       0   214.3      .1       0
Bank Sta=198.7,214.3
XS Rating Curve= 0 ,0
Exp/Cntr=0.3,0.1

Chan Stop Cuts=-1
Use User Specified Reach Order=0
Composite Channel Slope=5